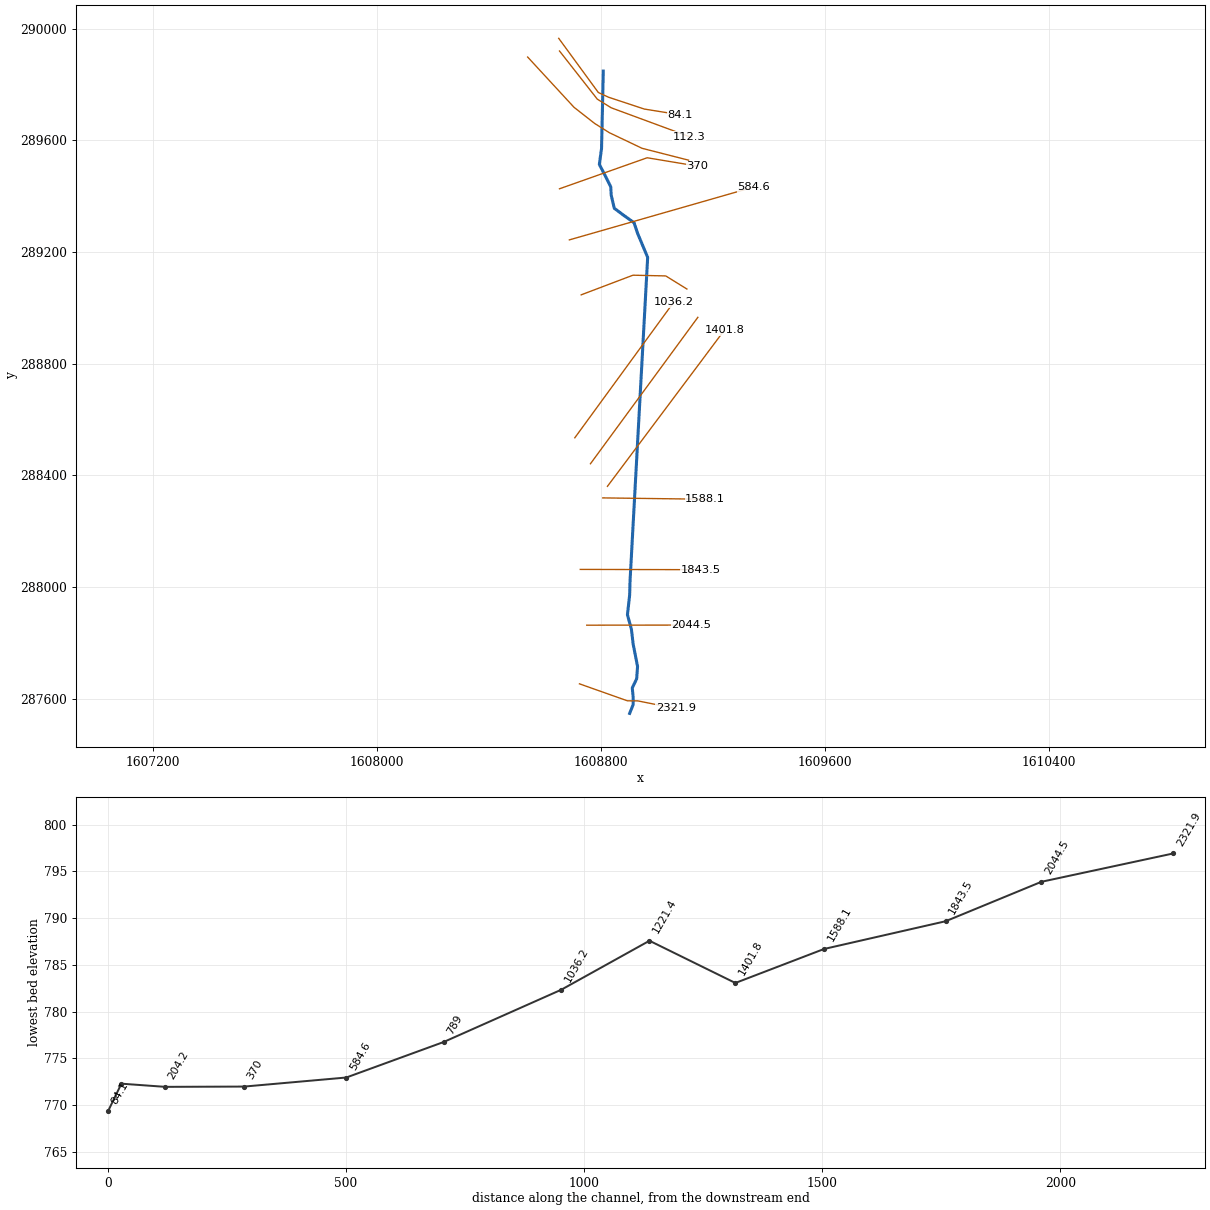
--- BRUSHYFK.prj (project) ---

Proj Title=BRUSHYFK
Current Plan=p01
Geom File=g01
Flow File=f01
Plan File=p01
DSS Export Rating Curves=0
DSS Export Rating Curve Sorted=0
DSS Export Volume Flow Curves=0
DXF OffsetX=0
DXF OffsetY=0
DXF ScaleX=0
DXF ScaleY=0

--- BRUSHYFK.p01 (plan) ---

Plan Title=Floodplain
Program Version=4.00
Geom File=g01
Flow File=f01
K Sum by GR=0
Std Step Tol=0.01
Critical Tol=0.01
Num of Std Step Trials=20
Max Error Tol=0.3
Flow Tol Ratio=0.001
Split Flow NTrial=30
Split Flow Tol=0.02
Split Flow Ratio=0.02
Log Output Level=0
Friction Slope Method=1
Unsteady Friction Slope Method=2
Unsteady Bridges Friction Slope Method=1
Global Log Level=0
CheckData=False
Run HTab=0
Run UNet=0
Run PostProcess=0
UNET Theta=0
UNET Theta Warmup=0
UNET ZTol=0
UNET ZSATol=0
UNET MxIter=0
UNET MaxInSteps=0
UNET DtIC=0
UNET DtMin=0
UNET MaxCRTS=0
UNET WFStab=0
UNET SFStab=0
UNET WFX=0
UNET SFX=0
UNET DSS MLevel=0
UNET DZMax Abort=0
UNET Convert EG Bridges=0
UNET Use Existing IB Tables=0
UNET Froude Limit=0
UNET Froude Power=0
Write IC File=0
Echo Input=False
Echo Output=False
Write Detailed=0

--- BRUSHYFK.f01 (steady flow) ---

Flow Title=NFF Regression Equation
Program Version=4.10
Number of Profiles= 1
Profile Names=P100yr
River Rch & RM=BRUSHYFK,Main            ,2321.9
503.0327
River Rch & RM=BRUSHYFK,Main            ,1588.1
 511.631
River Rch & RM=BRUSHYFK,Main            ,1036.2
566.1172
River Rch & RM=BRUSHYFK,Main            ,584.6
574.1147
River Rch & RM=BRUSHYFK,Main            ,204.2
576.5548
Boundary for River Rch & Prof#=BRUSHYFK,Main            , 1
Up Type= 0
Dn Type= 3
Dn Slope=0.02802
DSS Import GetInterval= 0
DSS Import GetPeak= 0
DSS Import FillOption= 0

--- BRUSHYFK.g01 (geometry) ---

Geom Title=USGS 10m DEM
Program Version=4.10

River Reach=BRUSHYFK        ,Main
Reach XY= 23
     1608902.706      287548.111     1608915.265      287579.509
     1608915.265      287606.197     1608912.125      287639.165
     1608927.824      287672.132     1608930.964      287716.089
     1608915.265      287796.153     1608908.985      287849.529
     1608894.856      287901.336     1608902.706       287971.98
     1608904.276      288026.299     1608907.416      288082.814
     1608967.071      289181.106     1608930.964       289267.45
     1608918.405      289305.127     1608879.157      289333.385
      1608847.76      289356.933     1608836.771       289404.03
     1608835.201      289433.858     1608811.652      289480.954
     1608794.384      289513.922     1608802.233      289570.438
     1608808.513      289848.307

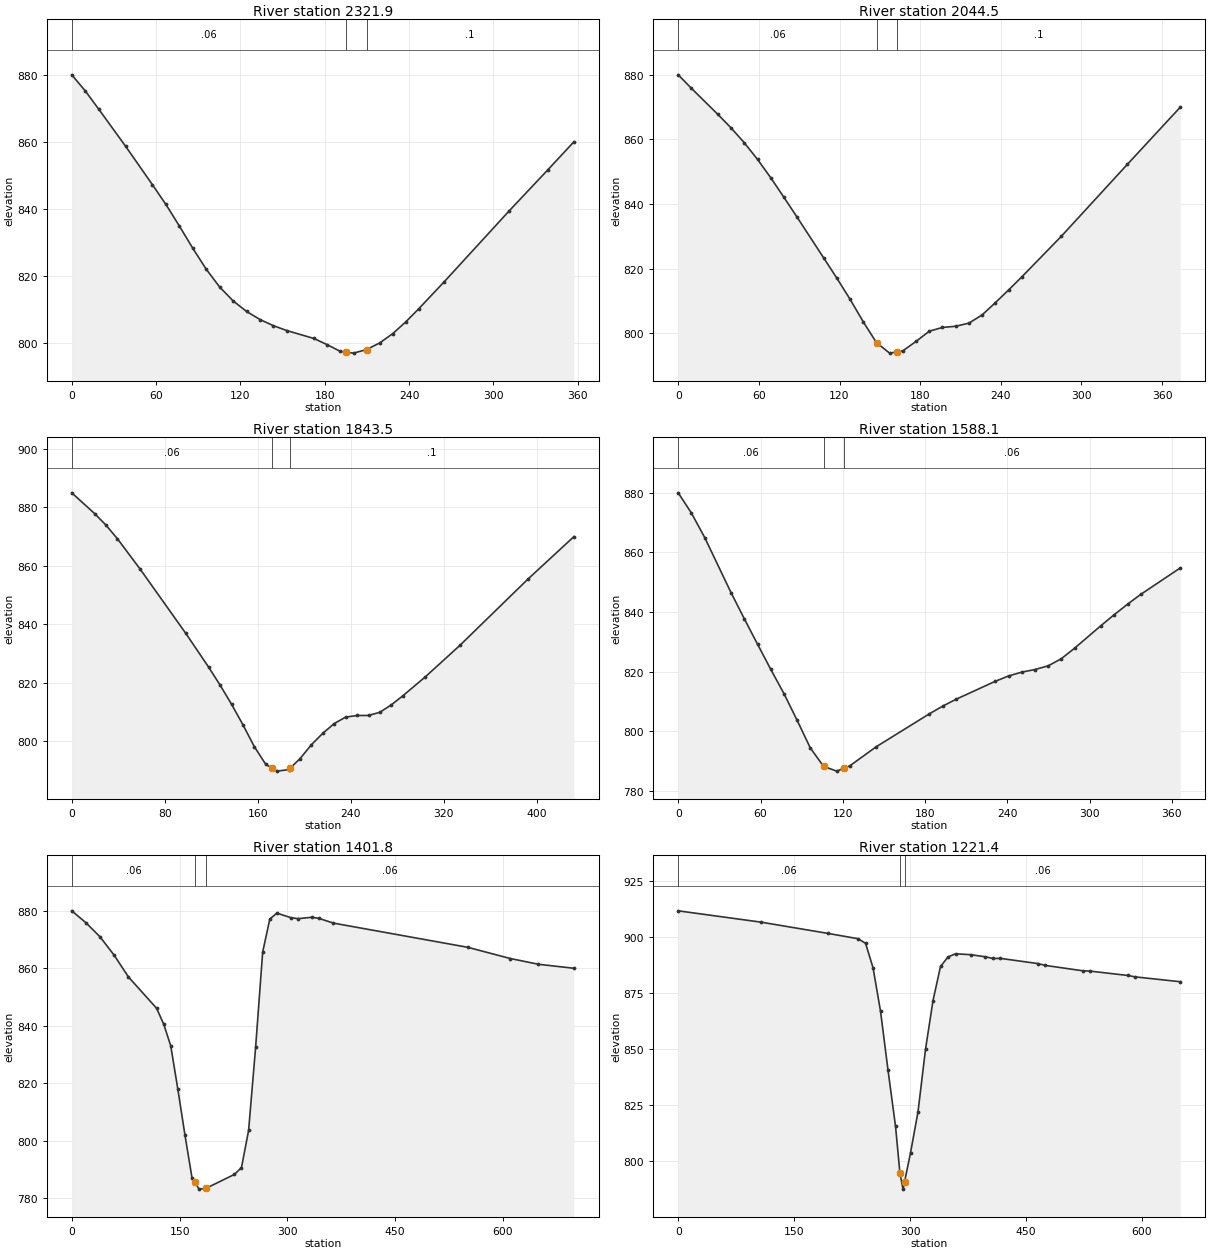
Type RM Length L Ch R = 1 ,2321.9  ,276.4,277.4,278.3
XS GIS Cut Line= 4
     1608723.403      287653.895     1608894.724      287593.103
     1608932.147      287592.787     1609067.502      287565.582
#Sta/Elev= 29
       0  880.01     9.6  875.21    19.1  869.81    38.3  858.69    57.4  847.21
      67  841.31    76.5  834.93    86.1  828.25    95.7  821.98   105.2  816.69
   114.8  812.53   124.4  809.37     134  806.95   143.5  805.12   153.1  803.66
   172.2  801.32   181.8  799.45   191.1  797.45   194.8  797.25   200.5  796.93
   209.8  797.99   219.2  799.99   228.4  802.75   237.6  806.22   246.8  810.12
   265.2   818.3   311.2  839.36   338.9   851.7   357.3     860
#Mann= 3 , 0 , 0
       0     .06       0   194.8    .045       0   209.8      .1       0
Bank Sta=194.8,209.8
XS Rating Curve= 0 ,0
Exp/Cntr=0.3,0.1

Type RM Length L Ch R = 1 ,2044.5  ,201.1,201,201
XS GIS Cut Line= 2
     1608749.569      287863.946     1609123.123      287864.404
#Sta/Elev= 30
       0     880     9.8  875.83    29.5  867.76    39.3  863.58    49.2  858.96
      59  853.84    68.8  848.18    78.6  842.13    88.5  835.92   108.1  823.44
     118   817.1   127.8   810.6   137.6  803.64   147.5  797.14   147.9  797.01
   157.3  793.89   162.9  794.28   167.1  794.58     177  797.53   186.8  800.67
   196.6  801.84   206.4   802.2   216.3  803.17   226.1   805.7   235.9  809.47
   245.8  813.42   255.6  817.46   285.1  830.06   334.2   852.3   373.6     870
#Mann= 3 , 0 , 0
       0     .06       0   147.9    .045       0   162.9      .1       0
Bank Sta=147.9,162.9
XS Rating Curve= 0 ,0
Exp/Cntr=0.3,0.1

Type RM Length L Ch R = 1 ,1843.5  ,255.6,255.4,255.1
XS GIS Cut Line= 2
     1608726.195      288063.659     1609157.991      288062.681
#Sta/Elev= 30
       0  885.02    19.6  877.93    29.4  873.97    39.2  869.32    58.9  858.83
    98.1  836.85   117.8  825.24   127.6  819.12   137.4  812.59   147.2  805.56
     157  798.06   166.8  792.01   172.6  790.63   176.6  789.67   186.5  790.18
   187.6   790.6   196.3  793.94   206.1  798.72   215.9  802.64   225.7  805.96
   235.5  808.17   245.3  808.73   255.2  808.74     265  809.83   274.8  812.38
   284.6  815.43   304.2  822.02   333.7  832.72   392.5  855.53   431.8     870
#Mann= 3 , 0 , 0
       0     .06       0   172.6    .045       0   187.6      .1       0
Bank Sta=172.6,187.6
XS Rating Curve= 0 ,0
Exp/Cntr=0.3,0.1

Type RM Length L Ch R = 1 ,1588.1  ,154.5,186.3,220.1
XS GIS Cut Line= 2
     1608806.737      288319.776      1609172.81      288314.961
#Sta/Elev= 30
       0     880     9.6  873.24    19.3  865.01    38.5  846.55    48.2  837.76
    57.8  829.27    67.4  820.88    77.1  812.68    86.7  803.73    96.3  794.48
     106  788.28   115.6   786.7     121  787.71   125.2   788.5   144.5  794.91
     183  805.88   192.7  808.45   202.3  810.73   231.2  816.82   240.9  818.61
   250.5  819.89   260.1  820.76   269.8     822   279.4  824.41     289  827.91
   308.3   835.5   317.9  839.14   327.6  842.65   337.2  845.94   366.1  854.83
#Mann= 3 , 0 , 0
       0     .06       0     106    .045       0     121     .06       0
Bank Sta=106,121
XS Rating Curve= 0 ,0
Exp/Cntr=0.3,0.1

Type RM Length L Ch R = 1 ,1401.8  ,179.4,180.4,180.9
XS GIS Cut Line= 2
     1608823.287      288361.088     1609241.459      288920.627
#Sta/Elev= 30
       0  880.01    19.7  875.86    39.4  870.93      59  864.54    78.7  857.02
   118.1  846.04   127.9  840.52   137.7  832.98   147.6  817.83   157.4  802.01
   167.2   787.1   171.3  785.43   177.1  783.06   186.3  783.29   226.3  788.19
   236.1  790.57     246  803.49   255.8  832.53   265.6  865.65   275.5  877.12
   285.3  879.23     305  877.61   314.8  877.28   334.5  877.78   344.4  877.34
     364  875.73     551   867.3     610   863.4   649.3  861.39   698.5     860
#Mann= 3 , 0 , 0
       0     .06       0   171.3    .045       0   186.3     .06       0
Bank Sta=171.3,186.3
XS Rating Curve= 0 ,0
Exp/Cntr=0.3,0.1

Type RM Length L Ch R = 1 ,1221.4  ,184.6,185.1,185
XS GIS Cut Line= 2
     1608762.728      288442.095     1609146.409        288966.4
#Sta/Elev= 30
       0  911.76   106.7  906.73   193.9  901.68   232.7  899.31   242.4  897.27
   252.1  886.33   261.8   866.9   271.5  840.55   281.2  815.56   286.9  794.66
   290.9  787.58   292.8  790.76   300.6  803.81   310.3  822.12     320  850.02
   329.7  871.74   339.4  886.94   349.1  891.15   358.8   892.6   378.2  892.19
   397.6  891.25   407.3  890.49     417  890.54   465.5  888.22   475.2  887.39
   523.6     885   533.3  884.85   581.8  882.91   591.5  882.28   649.7  880.12
#Mann= 3 , 0 , 0
       0     .06       0   286.9    .045       0   292.8     .06       0
Bank Sta=286.9,292.8
XS Rating Curve= 0 ,0
Exp/Cntr=0.3,0.1

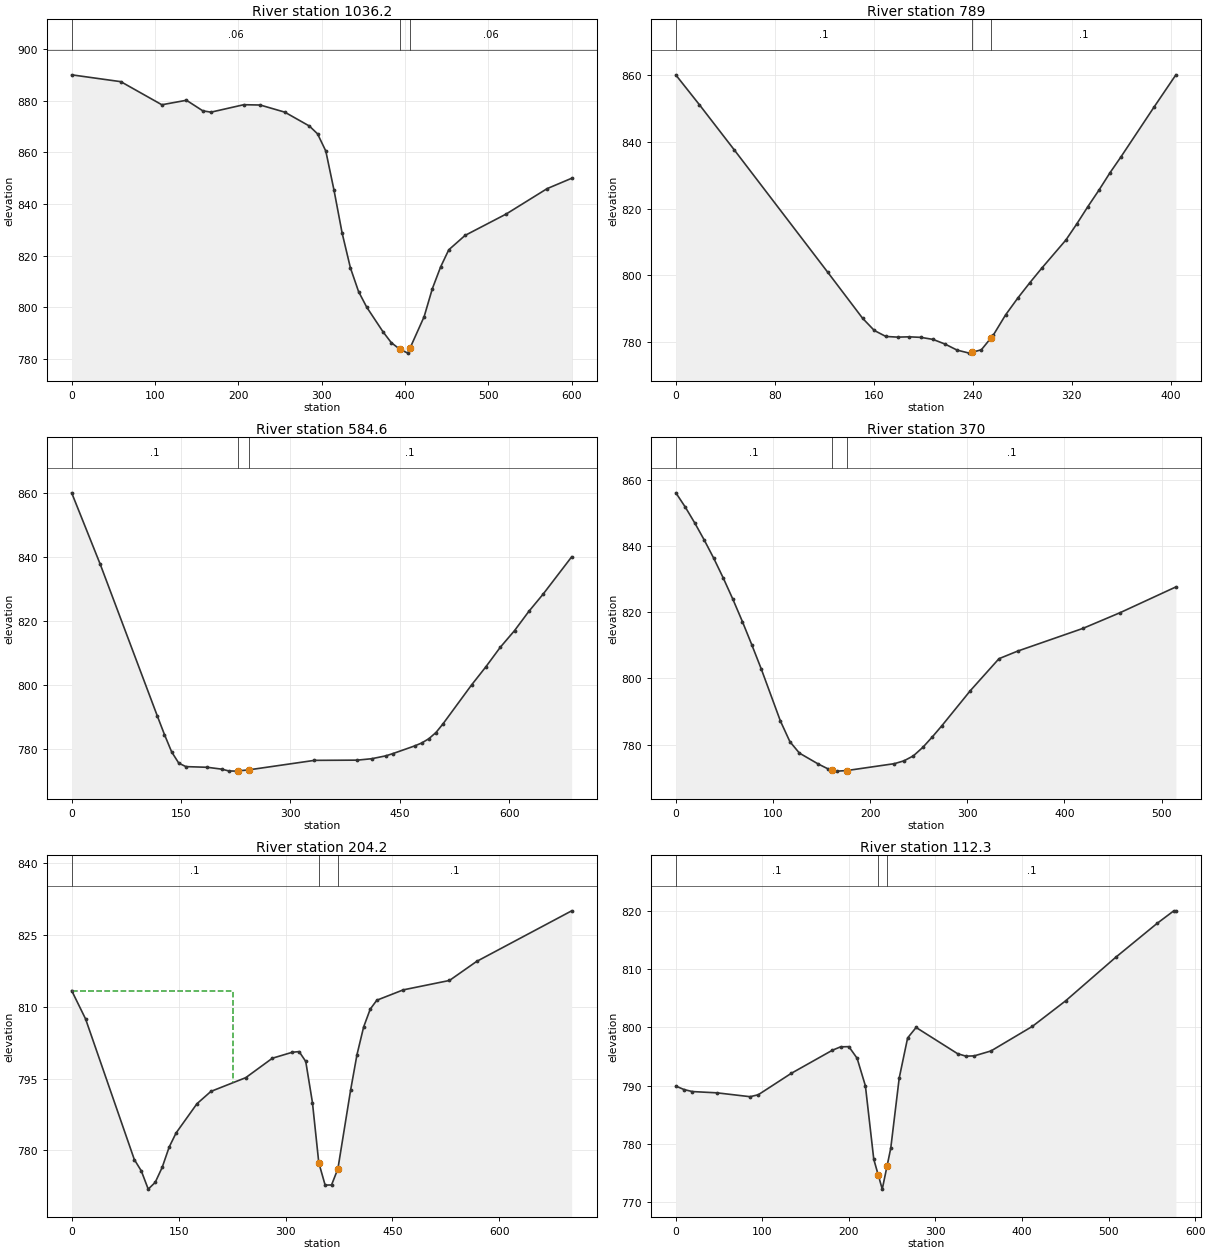
Type RM Length L Ch R = 1 ,1036.2  ,280.6,247.2,212.7
XS GIS Cut Line= 2
     1608706.854      288535.117     1609059.901      289020.132
#Sta/Elev= 30
       0     890      59  887.35   108.2  878.42   137.7  880.16   157.4  876.06
   167.2  875.56   206.5  878.44   226.2  878.32   255.7  875.56   285.2  870.19
     295  867.17   304.9  860.52   314.7  845.46   324.5  828.77   334.4  815.36
   344.2  806.16     354  800.11   373.7  790.52   383.5  786.38   393.4  783.92
   403.2  782.34   405.9  784.24   422.9  796.47   432.7  807.25   442.6  815.64
   452.4   822.3     472  827.88   521.2  836.13   570.4  845.97   599.9  849.99
#Mann= 3 , 0 , 0
       0     .06       0   393.4    .045       0   405.9     .06       0
Bank Sta=393.4,405.9
XS Rating Curve= 0 ,0
Exp/Cntr=0.3,0.1

Type RM Length L Ch R = 1 ,789     ,199.6,204.4,210.1
XS GIS Cut Line= 4
     1608729.458      289046.921     1608914.563      289117.262
     1609031.751      289114.658     1609107.271      289067.783
#Sta/Elev= 30
       0     860    18.9  851.16    47.2  837.58   122.6  801.02   150.9  787.18
   160.3  783.54   169.7  781.73   179.2  781.53   188.6  781.62     198  781.46
   207.8  780.85   217.6  779.44   227.3  777.64   237.1  776.74   239.5  776.99
   246.9  777.75   254.5  781.21   256.6  782.17   266.4  788.15   276.2  793.16
   285.9  797.74   295.7  802.17   315.2   810.6   324.1  815.47     333  820.62
   341.9  825.52   350.8  830.71   359.7  835.49   386.3  850.32   404.1  860.05
#Mann= 3 , 0 , 0
       0      .1       0   239.5    .045       0   254.5      .1       0
Bank Sta=239.5,254.5
XS Rating Curve= 0 ,0
Exp/Cntr=0.3,0.1

Type RM Length L Ch R = 1 ,584.6   ,211.4,214.6,217.2
XS GIS Cut Line= 2
     1608687.337      289243.769     1609346.371      289433.022
#Sta/Elev= 30
       0     860    39.2  837.64   117.5  790.17   127.3  784.36   137.1  778.96
   146.9  775.43   156.7  774.35   186.1  774.14   205.7  773.56   215.5     773
   225.3  772.94   227.7  772.99   242.7  773.33     333  776.31   391.8  776.38
   411.4  776.82     431  777.73   440.8  778.45   470.2  780.81     480  781.74
   489.8  783.08   499.6  785.02   509.4  787.78   548.5  799.93   568.1   805.6
   587.7  811.66   607.3  816.89   626.9   822.9   646.5   828.3   685.7  839.98
#Mann= 3 , 0 , 0
       0      .1       0   227.7    .045       0   242.7      .1       0
Bank Sta=227.7,242.7
XS Rating Curve= 0 ,0
Exp/Cntr=0.3,0.1

Type RM Length L Ch R = 1 ,370     ,187.8,165.8,143.6
XS GIS Cut Line= 3
     1608651.901      289426.677     1608965.344      289537.835
     1609145.032      289507.887
#Sta/Elev= 30
       0  856.05     9.8  851.69    19.6  846.87    29.3  841.74    39.1  836.22
    48.9  830.24    58.7  823.89    68.5  817.14    78.2  810.11      88  802.76
   107.6  787.12   117.4  780.86   127.2  777.41   146.7   774.1   156.5  772.67
   160.9  772.36   166.3  771.97   175.9  772.14     225  774.23   234.8  775.08
   244.5  776.59   254.3  779.18   264.1  782.35   273.9  785.72   303.2  796.31
   332.6  805.94   351.8  808.23   418.9  815.08   457.2  819.83   514.7  827.62
#Mann= 3 , 0 , 0
       0      .1       0   160.9    .045       0   175.9      .1       0
Bank Sta=160.9,175.9
XS Rating Curve= 0 ,0
Exp/Cntr=0.3,0.1

Type RM Length L Ch R = 1 ,204.2   ,93.8,91.9,92
XS GIS Cut Line= 6
     1608538.261      289898.512     1608703.626      289718.824
     1608777.209      289661.008     1608830.115      289627.623
     1608947.115      289571.689     1609113.269      289529.199
#Sta/Elev= 30
       0  813.36    19.5  807.45    87.9  778.11    97.7  775.74   107.4  771.94
   117.2  773.35     127  776.48   136.8  780.72   146.5  783.66   175.8  789.76
   195.4  792.33   244.2  795.19   281.6  799.25   309.7   800.5   319.1  800.63
   328.4  798.58   337.8     790   346.7  777.45   355.6  772.78   364.6  772.81
   373.5  776.18   391.4  792.64   400.3     800   409.6  805.76   418.9   809.5
   428.1  811.35   465.2  813.51     530  815.47   568.1  819.44   701.5     830
#Mann= 3 , 0 , 0
       0      .1       0   346.7    .045       0   373.5      .1       0
#XS Ineff= 2 , 0
          225.67  813.35
Permanent Ineff=
       F       F
Bank Sta=346.7,373.5
XS Rating Curve= 0 ,0
Exp/Cntr=0.3,0.1

Type RM Length L Ch R = 1 ,112.3   ,28.3,28.2,32
XS GIS Cut Line= 6
     1608651.998      289920.155     1608787.052      289747.808
     1608836.831      289716.772     1609116.098      289613.533
     1609117.282      289613.369     1609116.098      289613.533
#Sta/Elev= 30
       0  789.95     9.5  789.35      19  789.01    47.6  788.79    85.7  788.13
    95.2  788.46   133.3  792.13   180.9   796.1   190.4  796.68   199.9  796.71
   209.4  794.73     219     790   228.7  777.39   233.8  774.73   238.5  772.28
  243.94776.1658   248.3  779.28   258.1  791.34   267.8   798.2   277.6     800
   325.6   795.5   335.2  795.08   344.8  795.13   364.1  795.97   412.1   800.2
   450.5  804.58   508.1  812.01   556.2  817.86   575.4     820   577.8     820
#Mann= 3 , 0 , 0
       0      .1       0   233.8    .045       0  243.94      .1       0
Bank Sta=233.8,243.94
XS Rating Curve= 0 ,0
Exp/Cntr=0.3,0.1

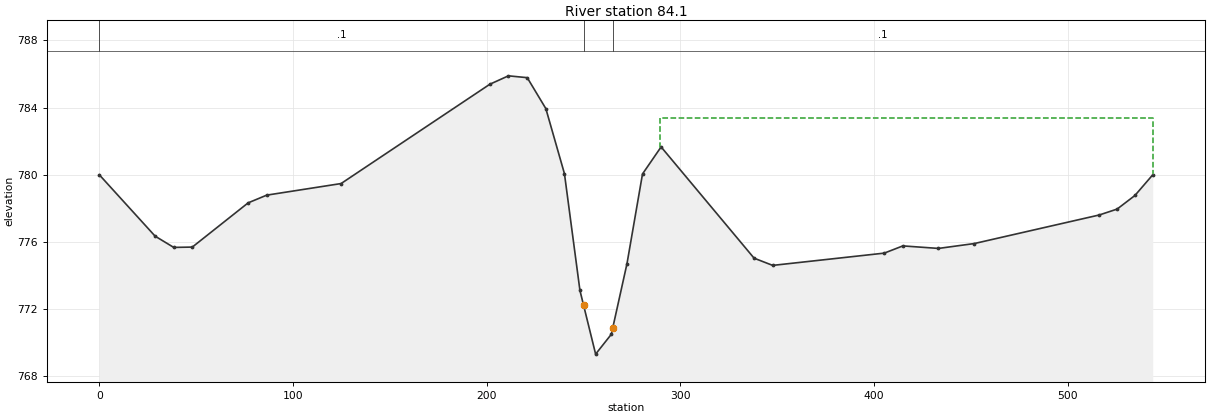
Type RM Length L Ch R = 1 ,84.1    ,68.7,84.1,93.7
XS GIS Cut Line= 5
     1608649.258      289965.501     1608790.745      289771.565
     1608827.373      289754.622     1608954.928      289712.314
     1609082.324      289691.787
#Sta/Elev= 30
       0     780    28.8  776.35    38.4  775.68      48   775.7    76.8  778.33
    86.4  778.79   124.8  779.48   201.6  785.39   211.2  785.89   220.9  785.78
   230.5  783.94   240.1  780.07   248.1  773.12     250  772.23   256.2  769.33
   264.3  770.51     265  770.87   272.4  774.72   280.4  780.05     290  781.66
     338  775.04   347.6  774.61   405.2  775.34   414.8  775.77   433.2  775.62
   451.7  775.91   516.2  777.61   525.4  777.96   534.6  778.77   543.8     780
#Mann= 3 , 0 , 0
       0      .1       0     250    .045       0     265      .1       0
#XS Ineff= 2 , 0
                          289.53          783.36
Permanent Ineff=
       F       F
Bank Sta=250,265
XS Rating Curve= 0 ,0
Exp/Cntr=0.3,0.1

Chan Stop Cuts=-1
Use User Specified Reach Order=0
Composite Channel Slope=5